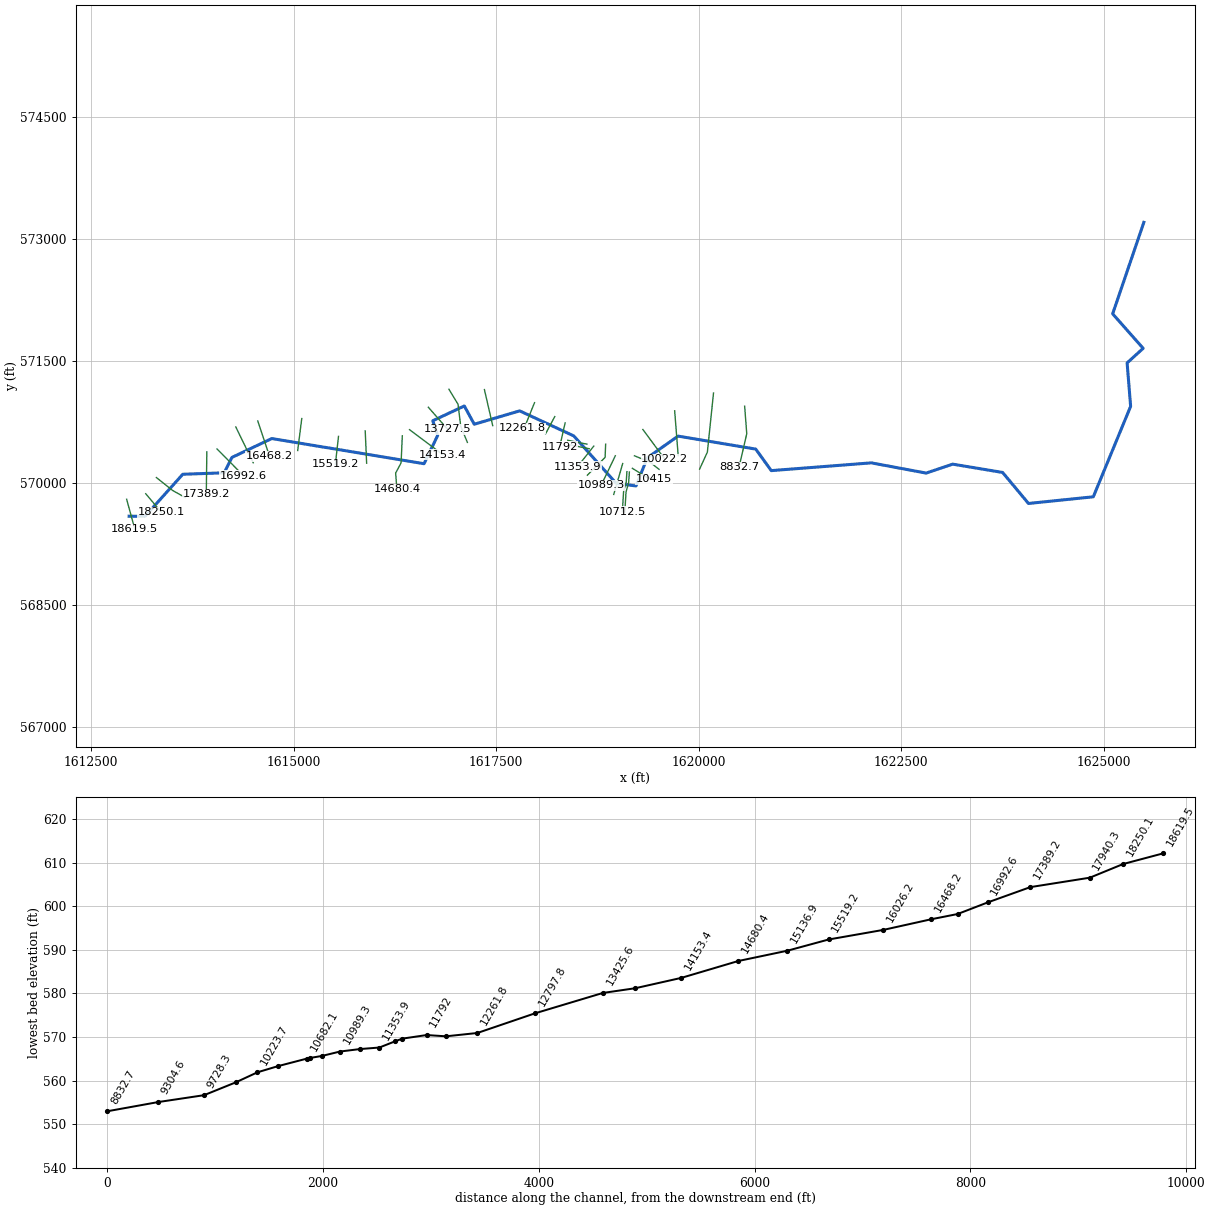
--- SpurlockCr.prj (project) ---

Proj Title=SpurlockCr
Current Plan=p01
Default Exp/Contr=0,0
English Units
Geom File=g01
Flow File=f01
Plan File=p01
BEGIN DESCRIPTION:
END DESCRIPTION:
DSS File=dss
DSS Export Rating Curves= 0
DSS Export Rating Curve Sorted= 0
DSS Export Volume Flow Curves= 0
DXF OffsetX= 0
DXF OffsetY= 0
DXF ScaleX= 0
DXF ScaleY= 0

--- SpurlockCr.p01 (plan) ---

Plan Title=Floodplain
Program Version=4.10
Short Identifier=Floodplain
Geom File=g01
Flow File=f01
Subcritical Flow
K Sum by GR= 0
Std Step Tol= 0.01
Critical Tol= 0.01
Num of Std Step Trials= 20
Max Error Tol= 0.3
Flow Tol Ratio= 0.001
Split Flow NTrial= 30
Split Flow Tol= 0.02
Split Flow Ratio= 0.02
Log Output Level= 0
Friction Slope Method= 1
Unsteady Friction Slope Method= 2
Unsteady Bridges Friction Slope Method= 1
Parabolic Critical Depth
Global Vel Dist= 0 , 0 , 0
Global Log Level= 0
CheckData=True
Encroach Param=-1 ,0,0, 0
Run HTab= 0
Run UNet= 0
Run PostProcess= 0
Run WQNet= 0
UNET Theta= 0
UNET Theta Warmup= 0
UNET ZTol= 0
UNET ZSATol= 0
UNET MxIter= 0
UNET MaxInSteps= 0
UNET DtIC= 0
UNET DtMin= 0
UNET MaxCRTS= 0
UNET WFStab= 0
UNET SFStab= 0
UNET WFX= 1
UNET SFX= 1
UNET DSS MLevel= 1
UNET DZMax Abort= 0
UNET Convert EG Bridges= 0
UNET Use Existing IB Tables= 0
UNET Froude Reduction=False
UNET Froude Limit= 0
UNET Froude Power= 0
UNET Time Slicing=0,0, 5
UNET Junction Losses=0
DSS File=dss
Write IC File= 0
Write IC File at Sim End=0
Echo Input=False
Echo Parameters=False
Echo Output=False
Write Detailed= 0
WQ AD Non Conservative
WQ ULTIMATE=-1
WQ Max Comp Step=1HOUR
WQ Output Interval=15MIN
WQ Output Selected Increments= 0
WQ Output face flow=0
WQ Output face velocity=0
WQ Output face area=0
WQ Output face dispersion=0
WQ Output cell volume=0
WQ Output cell surface area=0
WQ Output cell continuity=0
WQ Output cumulative cell continuity=0
WQ Output face conc=0
WQ Output face dconc_dx=0
WQ Output face courant=0
WQ Output face peclet=0
WQ Output face adv mass=0
WQ Output face disp mass=0
WQ Output cell mass=0
WQ Output cell source sink temp=0
WQ Output cell source sink nsm=0
WQ Output MaxMinRange=-1
WQ Daily Max Min Mean=-1
WQ Daily Range=0
WQ Daily Time=0
WQ Create Restart=0
WQ Fixed Restart=0
WQ System Summary=0
WQ Use Fixed Temperature=0
Sorting and Armoring Iterations= 10
XS Update Threshold= 0.02
Hydraulics Update Threshold= 0.02
Energy Slope Method= 1
Volume Change Method= 0
XS Weighting Method= 0
Number of US Weighted Cross Sections= 1
Number of DS Weighted Cross Sections= 1
Upstream XS Weight=0.25
Main XS Weight=0.5
Downstream XS Weight=0.25
Number of DS XS's Weighted with US Boundary= 1
Upstream Boundary Weight= 1
Weight of XSs Associated with US Boundary= 0
Number of US XS's Weighted with DS Boundary= 1
Downstream Boundary Weight= 0.5
Weight of XSs Associated with DS Boundary= 0.5
Sediment Output Level= 4
Mass or Volume Output= 0
Output Increment Type= 1
Profile and TS Output Increment= 10
XS Output Flag= 0
XS Output Increment= 10
Disregard all LS=0
Disregard all Conn=0
Disregard all Breaches=0
Disregard all Pumps=0

--- SpurlockCr.f01 (steady flow) ---

Flow Title=NFF Regression Equation
Program Version=4.10
Number of Profiles= 1
Profile Names=P100yr
River Rch & RM=SpurlockCr,Main            ,18619.5
     962
River Rch & RM=SpurlockCr,Main            ,17389.2
     993
River Rch & RM=SpurlockCr,Main            ,16714.8
    1034
River Rch & RM=SpurlockCr,Main            ,15519.2
    1080
River Rch & RM=SpurlockCr,Main            ,14153.4
    1096
River Rch & RM=SpurlockCr,Main            ,13425.6
    1111
River Rch & RM=SpurlockCr,Main            ,12797.8
    1223
River Rch & RM=SpurlockCr,Main            ,12261.8
    1231
River Rch & RM=SpurlockCr,Main            ,11353.9
    1240
River Rch & RM=SpurlockCr,Main            ,10989.3
    1243
River Rch & RM=SpurlockCr,Main            ,10022.2
    1323
River Rch & RM=SpurlockCr,Main            ,9728.3
    1433
River Rch & RM=SpurlockCr,Main            ,8832.7
    1442
Boundary for River Rch & Prof#=SpurlockCr,Main            , 1
Up Type= 0
Dn Type= 3
Dn Slope=0.00465
DSS Import GetInterval= 0
DSS Import GetPeak= 0
DSS Import FillOption= 0

--- SpurlockCr.g01 (geometry) ---

Geom Title=USGS 10m DEM
Program Version=4.10

River Reach=SpurlockCr      ,Main
Reach XY= 30
     1612969.527      569588.276     1613166.118      569586.655
     1613631.948      570103.688     1614143.298      570121.737
     1614238.669      570310.795     1614730.582      570542.971
     1616610.114      570233.476     1616778.815      570581.271
     1616717.722      570761.265     1617107.593      570943.391
      1617229.77       570718.62     1617790.583      570882.918
     1618457.941      570575.507       1618983.7      569990.374
     1619226.297      569960.391     1619366.182      570305.973
     1619745.382      570572.753     1620704.645         570413.
     1620896.306      570148.483     1622131.115      570243.969
     1622808.199      570118.101     1623135.635      570228.104
     1623751.501      570126.251      1624071.22      569744.837
     1624871.292      569826.772      1625332.07      570938.414
     1625288.668      571472.268     1625486.697      571651.732
     1625110.263      572075.579     1625495.109      573200.201

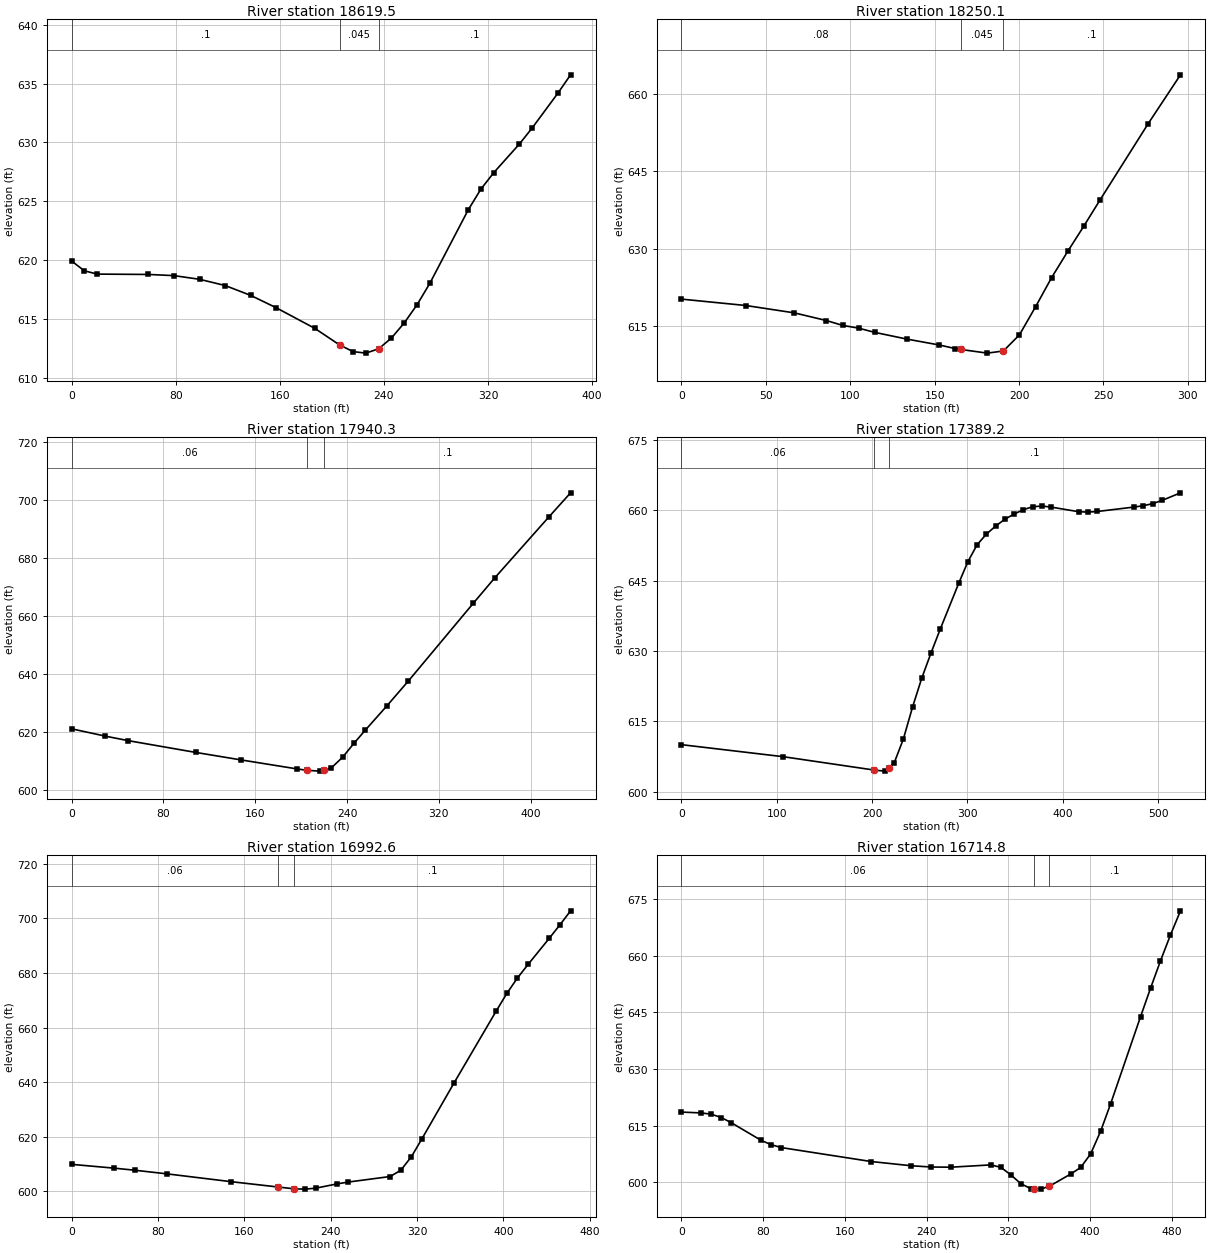
Type RM Length L Ch R = 1 ,18619.5 ,358.7,369.4,379.9
XS GIS Cut Line= 2
      1612939.24      569796.396     1613040.802      569426.605
#Sta/Elev= 25
       0  619.93     9.8   619.1    19.7  618.82      59  618.79    78.7  618.69
    98.3  618.38     118  617.85   137.7  617.01   157.3  615.96   186.8  614.22
   205.9  612.81   216.3  612.24   226.2  612.11     236  612.48   245.8  613.39
   255.7  614.68   265.5  616.22   275.3  618.03   304.8  624.27   314.6  626.04
   324.5  627.44   344.2  629.87     354  631.23   373.6  634.16   383.5  635.74
#Mann= 3 , 0 , 0
       0      .1       0   205.9    .045       0     236      .1       0
Bank Sta=205.9,236
XS Rating Curve= 0 ,0
Exp/Cntr=0.3,0.1

Type RM Length L Ch R = 1 ,18250.1 ,303.7,309.8,314.8
XS GIS Cut Line= 2
     1613174.917      569864.105     1613366.323      569638.844
#Sta/Elev= 21
       0  620.18    38.1  618.94    66.8  617.51    85.8  616.02    95.4  615.08
   104.9  614.54   114.4  613.72   133.5  612.41   152.6  611.27   162.1  610.57
   165.5  610.39   181.2  609.68   190.7   610.1   200.2  613.23   209.8  618.72
   219.3  624.38   228.8  629.46   238.4   634.4   247.9  639.44   276.5  654.31
   295.6  663.79
#Mann= 3 , 0 , 0
       0     .08       0   165.5    .045       0   190.7      .1       0
Bank Sta=165.5,190.7
XS Rating Curve= 0 ,0
Exp/Cntr=0.3,0.1

Type RM Length L Ch R = 1 ,17940.3 ,571.9,551.1,530.2
XS GIS Cut Line= 3
     1613306.427      570063.323     1613506.948      569904.469
     1613663.198       569817.23
#Sta/Elev= 19
       0  621.13    29.5   618.6    49.2  617.06   108.2  612.99   147.6  610.41
   196.8  607.28   205.2  606.81   216.5  606.54   220.2  606.96   226.3  607.65
   236.1  611.31     246  616.12   255.8  620.62   274.7  629.04   293.5  637.65
     350  664.43   368.8  673.23   415.9  694.22   434.8  702.53
#Mann= 3 , 0 , 0
       0     .06       0   205.2    .045       0   220.2      .1       0
Bank Sta=205.2,220.2
XS Rating Curve= 0 ,0
Exp/Cntr=0.3,0.1

Type RM Length L Ch R = 1 ,17389.2 ,377.2,396.6,415.3
XS GIS Cut Line= 2
     1613928.823       570379.73     1613922.313      569856.292
#Sta/Elev= 30
       0  610.02   106.6  607.46   202.4   604.6   213.3  604.38   217.4  605.09
     223  606.06   232.7  611.18   242.4  618.03     252  624.16   261.7  629.53
   271.4  634.62   290.8   644.4   300.5  649.05   310.2  652.66   319.9  654.91
   329.6  656.63   339.3  658.08     349  659.19   358.7  660.12   368.4  660.74
   378.1  660.89   387.8  660.67   416.8  659.68   426.5   659.6   436.2  659.73
     475  660.68   484.7  660.97   494.4  661.41   504.1  662.08   523.5  663.71
#Mann= 3 , 0 , 0
       0     .06       0   202.4    .045       0   217.4      .1       0
Bank Sta=202.4,217.4
XS Rating Curve= 0 ,0
Exp/Cntr=0.3,0.1

Type RM Length L Ch R = 1 ,16992.6 ,285.2,277.8,270
XS GIS Cut Line= 2
     1614055.125      570414.886     1614380.646      570086.761
#Sta/Elev= 23
       0  609.93    39.3  608.54      59  607.76    88.5  606.44   147.5   603.6
   191.4  601.63   206.4  600.96   216.4  600.86   226.2  601.22   245.8  602.76
   255.7  603.42     295  605.47   304.9  607.75   314.7   612.7   324.5  619.27
     354  639.55   393.4   666.1   403.2  672.51     413  678.15   422.9  683.13
   442.5  692.68   452.4  697.62   462.2  702.71
#Mann= 3 , 0 , 0
       0     .06       0   191.4    .045       0   206.4      .1       0
Bank Sta=191.4,206.4
XS Rating Curve= 0 ,0
Exp/Cntr=0.3,0.1

Type RM Length L Ch R = 1 ,16714.8 ,250.3,246.6,242.8
XS GIS Cut Line= 2
     1614286.896      570684.417      1614501.74      570245.615
#Sta/Elev= 30
       0  618.59    19.5  618.36    29.3  618.02    39.1  617.13    48.9  615.75
    78.2  611.08    87.9  609.96    97.7   609.2   185.7  605.51   224.7   604.4
   244.3  604.06   263.8  604.01   302.9  604.62   312.7  603.98   322.5  601.98
   332.2  599.67     342  598.34   345.3   598.3   351.8  598.21   360.3  598.99
   381.1   602.2   390.9  603.94   400.6  607.51   410.4  613.51   420.2  620.77
   449.5  643.82   459.3  651.36     469  658.56   478.8  665.44   488.6  671.82
#Mann= 3 , 0 , 0
       0     .06       0   345.3    .045       0   360.3      .1       0
Bank Sta=345.3,360.3
XS Rating Curve= 0 ,0
Exp/Cntr=0.3,0.1

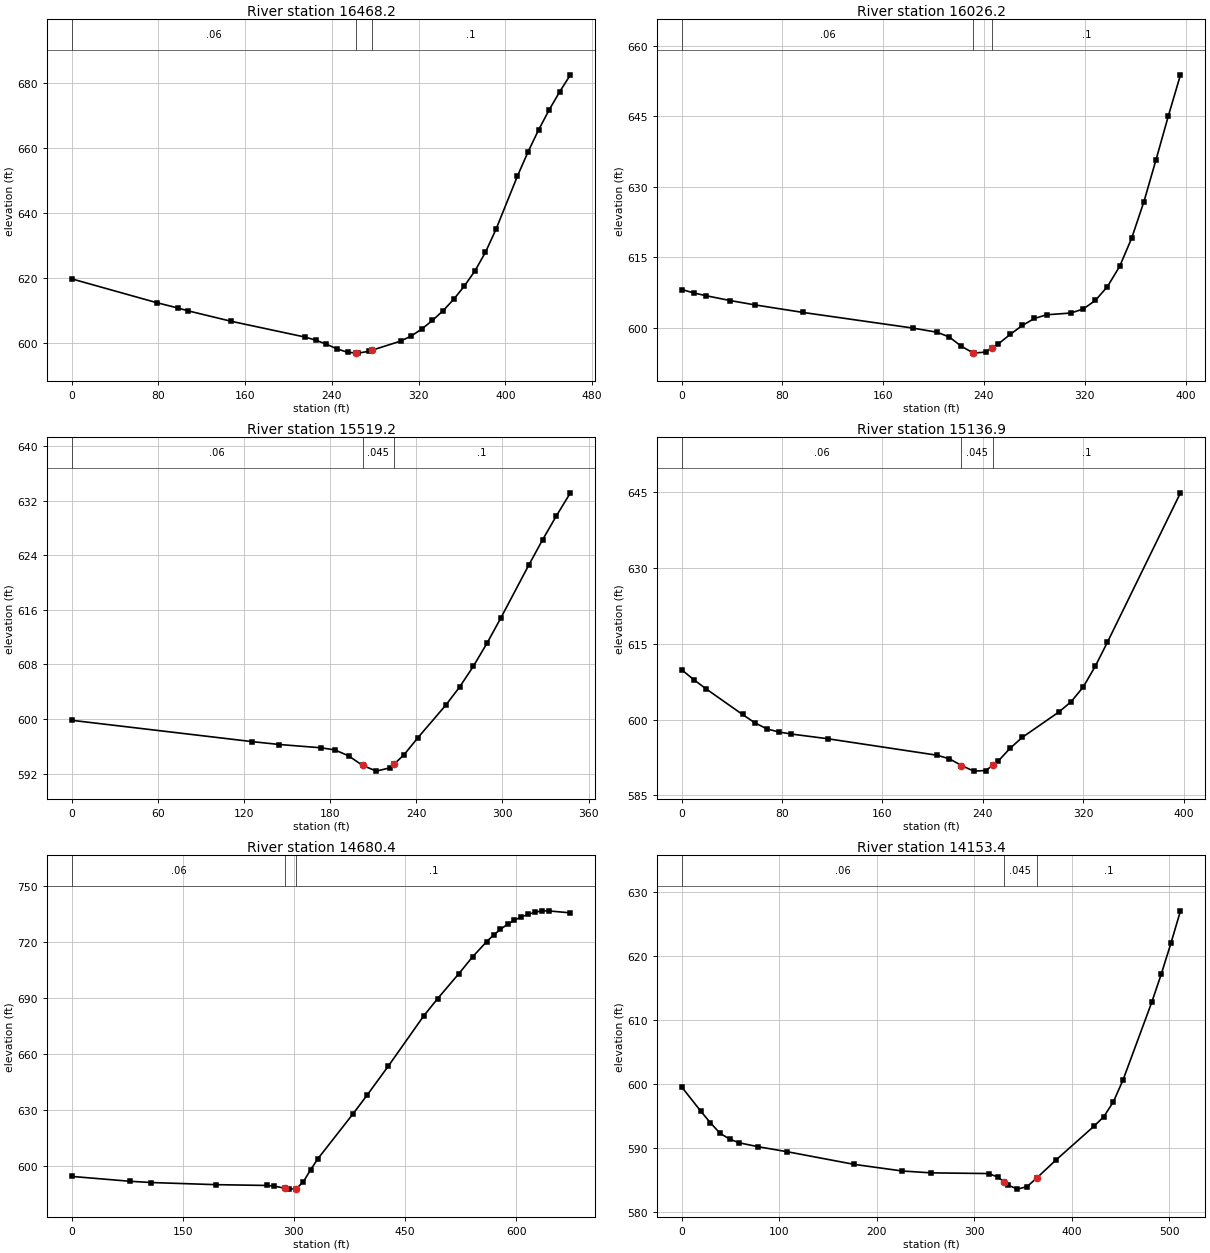
Type RM Length L Ch R = 1 ,16468.2 ,451.6,442,432.4
XS GIS Cut Line= 2
     1614557.729      570758.636     1614703.563      570322.438
#Sta/Elev= 30
       0  619.83    78.3  612.52    97.9  610.88   107.6  609.98   146.8  606.81
   215.3  601.93   225.1  600.99   234.9  599.74   244.6  598.32   254.4  597.26
   261.8  597.06   264.2     597     274  597.56   276.8  597.88   303.4   600.7
   313.1  602.25   322.9  604.42   332.7  607.05   342.5  610.04   352.3  613.55
   362.1  617.62   371.9  622.28   381.6  628.02   391.4  635.15     411  651.37
   420.8  658.84   430.6  665.64   440.4  671.81   450.1  677.38   459.9  682.53
#Mann= 3 , 0 , 0
       0     .06       0   261.8    .045       0   276.8      .1       0
Bank Sta=261.8,276.8
XS Rating Curve= 0 ,0
Exp/Cntr=0.3,0.1

Type RM Length L Ch R = 1 ,16026.2 ,506.7,507,507.1
XS GIS Cut Line= 2
     1615100.698      570788.584     1615050.785      570395.789
#Sta/Elev= 29
       0  608.13     9.7  607.39    19.3  606.81    38.6  605.77    57.9  604.86
    96.6  603.23   183.5  599.91   202.8  599.02   212.5     598   222.1  596.02
   231.5  594.61   231.8  594.57   241.4   594.8   246.5  595.67   251.1  596.46
   260.8  598.56   270.4  600.46   280.1  601.96   289.7  602.74     309  603.12
   318.7  603.96   328.4  605.79     338  608.74   347.7  613.05   357.3   619.1
     367  626.87   376.6  635.79   386.3  645.05     396  653.88
#Mann= 3 , 0 , 0
       0     .06       0   231.5    .045       0   246.5      .1       0
Bank Sta=231.5,246.5
XS Rating Curve= 0 ,0
Exp/Cntr=0.3,0.1

Type RM Length L Ch R = 1 ,15519.2 ,377.8,382.3,385.7
XS GIS Cut Line= 2
     1615554.257        570569.4     1615515.194      570224.348
#Sta/Elev= 21
       0  599.82   125.4   596.7   144.7  596.27   173.6  595.79   183.3  595.48
   192.9   594.6   202.6  593.21   212.2  592.37   221.9  592.87   224.4  593.37
   231.5  594.78   241.2  597.29   260.4  602.01   270.1  604.68   279.7  607.73
   289.4  611.18     299  614.87   318.3  622.56     328   626.3   337.6   629.8
   347.3  633.15
#Mann= 3 , 0 , 0
       0     .06       0   202.6    .045       0   224.4      .1       0
Bank Sta=202.6,224.4
XS Rating Curve= 0 ,0
Exp/Cntr=0.3,0.1

Type RM Length L Ch R = 1 ,15136.9 ,458.6,456.6,454.2
XS GIS Cut Line= 2
     1615884.118      570636.674     1615901.479      570239.539
#Sta/Elev= 24
       0  609.82     9.7  607.87    19.4  606.07    48.5  600.99    58.2  599.37
    67.9  598.14    77.6  597.53    87.3  597.13   116.4   596.2   203.6  592.94
   213.3  592.24     223  590.91   232.7   589.8   242.4  589.92   248.3  591.03
   252.1  591.75   261.8  594.33   271.5  596.48   300.6  601.48   310.3   603.5
     320  606.42   329.6  610.52   339.3  615.28   397.5  644.79
#Mann= 3 , 0 , 0
       0     .06       0     223    .045       0   248.3      .1       0
Bank Sta=223,248.3
XS Rating Curve= 0 ,0
Exp/Cntr=0.3,0.1

Type RM Length L Ch R = 1 ,14680.4 ,504.1,527,550
XS GIS Cut Line= 4
     1616342.017       570575.91     1616326.826      570243.879
     1616259.552      570118.011     1616274.743      569920.528
#Sta/Elev= 30
       0  594.26    78.2  591.66   107.5  590.97   195.5  589.82     264   589.4
   273.7  589.08   288.2  587.84   293.3  587.43   303.2  587.69   312.8  591.38
   322.6  597.84   332.4  603.76     380  627.94     399  637.98   427.5  653.52
   475.1  680.37     494   689.7   522.3  702.95   541.1   712.1     560  720.23
   569.4  723.78   578.8   726.9   588.3  729.61   597.7  731.85   607.1  733.59
   616.6     735     626  736.17   635.4  736.84   644.9  736.76   673.2  735.75
#Mann= 3 , 0 , 0
       0     .06       0   288.2    .045       0   303.2      .1       0
Bank Sta=288.2,303.2
XS Rating Curve= 0 ,0
Exp/Cntr=0.3,0.1

Type RM Length L Ch R = 1 ,14153.4 ,430.5,425.9,421.2
XS GIS Cut Line= 2
     1616430.993      570651.865     1616841.149      570345.876
#Sta/Elev= 27
       0  599.53    19.7  595.72    29.5  593.92    39.4  592.28    49.2  591.38
      59   590.8    78.7  590.18   108.2  589.41   177.1  587.43   226.3   586.4
   255.9  586.11   314.9     586   324.8  585.42   330.2  584.76   334.6  584.22
   344.4  583.57   354.3  583.96   364.1  585.28   383.8  588.09   423.2  593.42
     433  594.87   442.8  597.18   452.7  600.58   482.2  612.72     492  617.14
   501.9  621.95   511.7  627.01
#Mann= 3 , 0 , 0
       0     .06       0   330.2    .045       0   364.1      .1       0
Bank Sta=330.2,364.1
XS Rating Curve= 0 ,0
Exp/Cntr=0.3,0.1

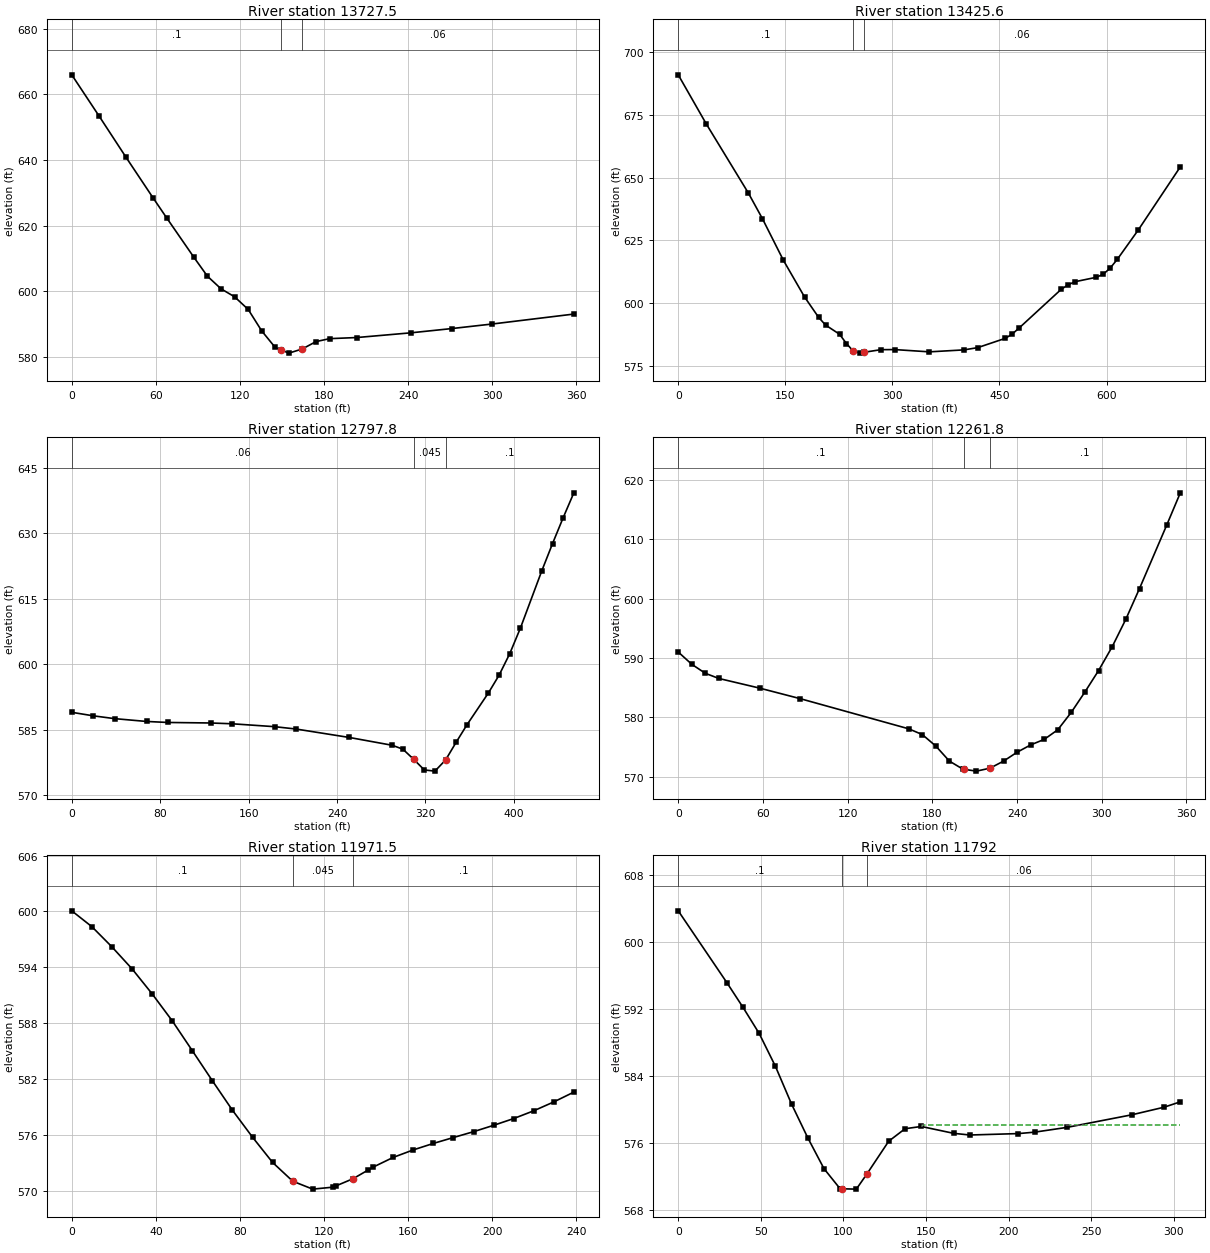
Type RM Length L Ch R = 1 ,13727.5 ,316,301.9,287.7
XS GIS Cut Line= 2
     1616663.198      570927.473     1616899.743      570658.376
#Sta/Elev= 22
       0  665.99    19.4  653.49    38.7  640.88    58.1  628.45    67.8  622.36
    87.2  610.37    96.8  604.64   106.5   600.8   116.2  598.36   125.9  594.51
   135.6  587.94   145.2  582.92   149.4  582.18   154.9   581.2   164.4  582.45
   174.3  584.71     184  585.61   203.4  585.95   242.1  587.39   271.1  588.68
   300.2  590.08   358.3   593.1
#Mann= 3 , 0 , 0
       0      .1       0   149.4    .045       0   164.4     .06       0
Bank Sta=149.4,164.4
XS Rating Curve= 0 ,0
Exp/Cntr=0.3,0.1

Type RM Length L Ch R = 1 ,13425.6 ,624.1,627.8,631.6
XS GIS Cut Line= 4
     1616917.104      571148.827     1617029.951      570964.365
     1617062.504      570695.268     1617144.969      570495.615
#Sta/Elev= 30
       0  690.97    39.3   671.4    98.3  643.85     118  633.63   147.4  617.04
   176.9   602.5   196.6  594.38   206.4  591.28   225.9  587.65   235.6  583.94
   244.6   581.1     255  580.11   259.6  580.42     284  581.49   303.4  581.52
   351.8  580.62   400.2   581.4   419.5   582.3   458.3  586.02   467.9  587.72
   477.6  590.14   536.4  605.51   546.2  607.35     556  608.57   585.5  610.31
   595.3  611.52   605.1     614     615  617.46   644.4  629.16   703.3  654.31
#Mann= 3 , 0 , 0
       0      .1       0   244.6    .045       0   259.6     .06       0
Bank Sta=244.6,259.6
XS Rating Curve= 0 ,0
Exp/Cntr=0.3,0.1

Type RM Length L Ch R = 1 ,12797.8 ,550.2,536,521.6
XS GIS Cut Line= 2
     1617355.472      571144.487     1617457.469      570701.778
#Sta/Elev= 26
       0  588.95    19.3  588.15    38.7   587.5    67.7  586.85      87  586.62
   125.7   586.5     145  586.32   183.7  585.65     203  585.11   251.3  583.17
     290  581.38   299.6  580.49   309.3  578.18     319  575.72   328.6  575.45
   338.3  578.03     348  582.16   357.6  586.09     377   593.4   386.6  597.45
   396.3  602.41     406  608.32   425.3  621.43     435  627.67   444.6   633.6
   454.3  639.33
#Mann= 3 , 0 , 0
       0     .06       0   309.3    .045       0   338.3      .1       0
Bank Sta=309.3,338.3
XS Rating Curve= 0 ,0
Exp/Cntr=0.3,0.1

Type RM Length L Ch R = 1 ,12261.8 ,292.6,290.3,287.6
XS GIS Cut Line= 3
     1617973.962      570983.896     1617865.455      570716.969
     1617819.882      570667.056
#Sta/Elev= 27
       0     591     9.6  588.93    19.2  587.41    28.8  586.54    57.6  584.92
    86.4  583.14   163.3  578.06   172.9  577.09   182.5  575.15   192.1  572.62
   201.7  571.26   202.3  571.24   211.3  570.93   220.9  571.43   230.5  572.62
   240.1  574.12   249.7  575.35   259.3  576.28   268.9   577.9   278.5  580.85
   288.1  584.26   297.8  587.88   307.4  591.87   317.1  596.52   326.8   601.7
   346.1   612.4   355.7  617.82
#Mann= 3 , 0 , 0
       0      .1       0   202.3    .045       0   220.9      .1       0
Bank Sta=202.3,220.9
XS Rating Curve= 0 ,0
Exp/Cntr=0.3,0.1

Type RM Length L Ch R = 1 ,11971.5 ,173.3,179.5,185.6
XS GIS Cut Line= 2
     1618223.528      570812.455     1618110.681      570601.952
#Sta/Elev= 28
       0  600.06     9.6  598.35    19.1  596.19    28.7  593.82    38.2  591.15
    47.8  588.24    57.3  585.05    66.9   581.8    76.4  578.65      86  575.74
    95.5  573.04   105.1  571.02   114.6  570.17   124.2  570.38   125.8  570.53
   133.8  571.29   140.8   572.2   143.3  572.53   152.9  573.58   162.4  574.38
     172  575.08   181.5  575.71   191.1  576.34   200.6  577.02   210.2  577.75
   219.7  578.58   229.3  579.54   238.8  580.59
#Mann= 3 , 0 , 0
       0      .1       0   105.1    .045       0   133.8      .1       0
Bank Sta=105.1,133.8
XS Rating Curve= 0 ,0
Exp/Cntr=0.3,0.1

Type RM Length L Ch R = 1 ,11792   ,263.2,225,186.7
XS GIS Cut Line= 2
     1618351.566       570734.33     1618283.725      570438.071
#Sta/Elev= 23
       0  603.68    29.4  595.12    39.2  592.16      49  589.04    58.8  585.13
    68.6  580.61    78.4  576.59    88.2  572.91      98   570.5    99.1   570.5
   107.8  570.46   114.1  572.24   127.4  576.18   137.3  577.67   147.1  577.94
   166.7  577.12   176.5  576.92   205.9  577.09   215.7  577.26   235.3  577.83
   274.5  579.33   294.1  580.24   303.9  580.88
#Mann= 3 , 0 , 0
       0      .1       0    99.1    .045       0   114.1     .06       0
#XS Ineff= 2 , 0
                          147.39          578.06
Permanent Ineff=
       F       F
Bank Sta=99.1,114.1
XS Rating Curve= 0 ,0
Exp/Cntr=0.3,0.1

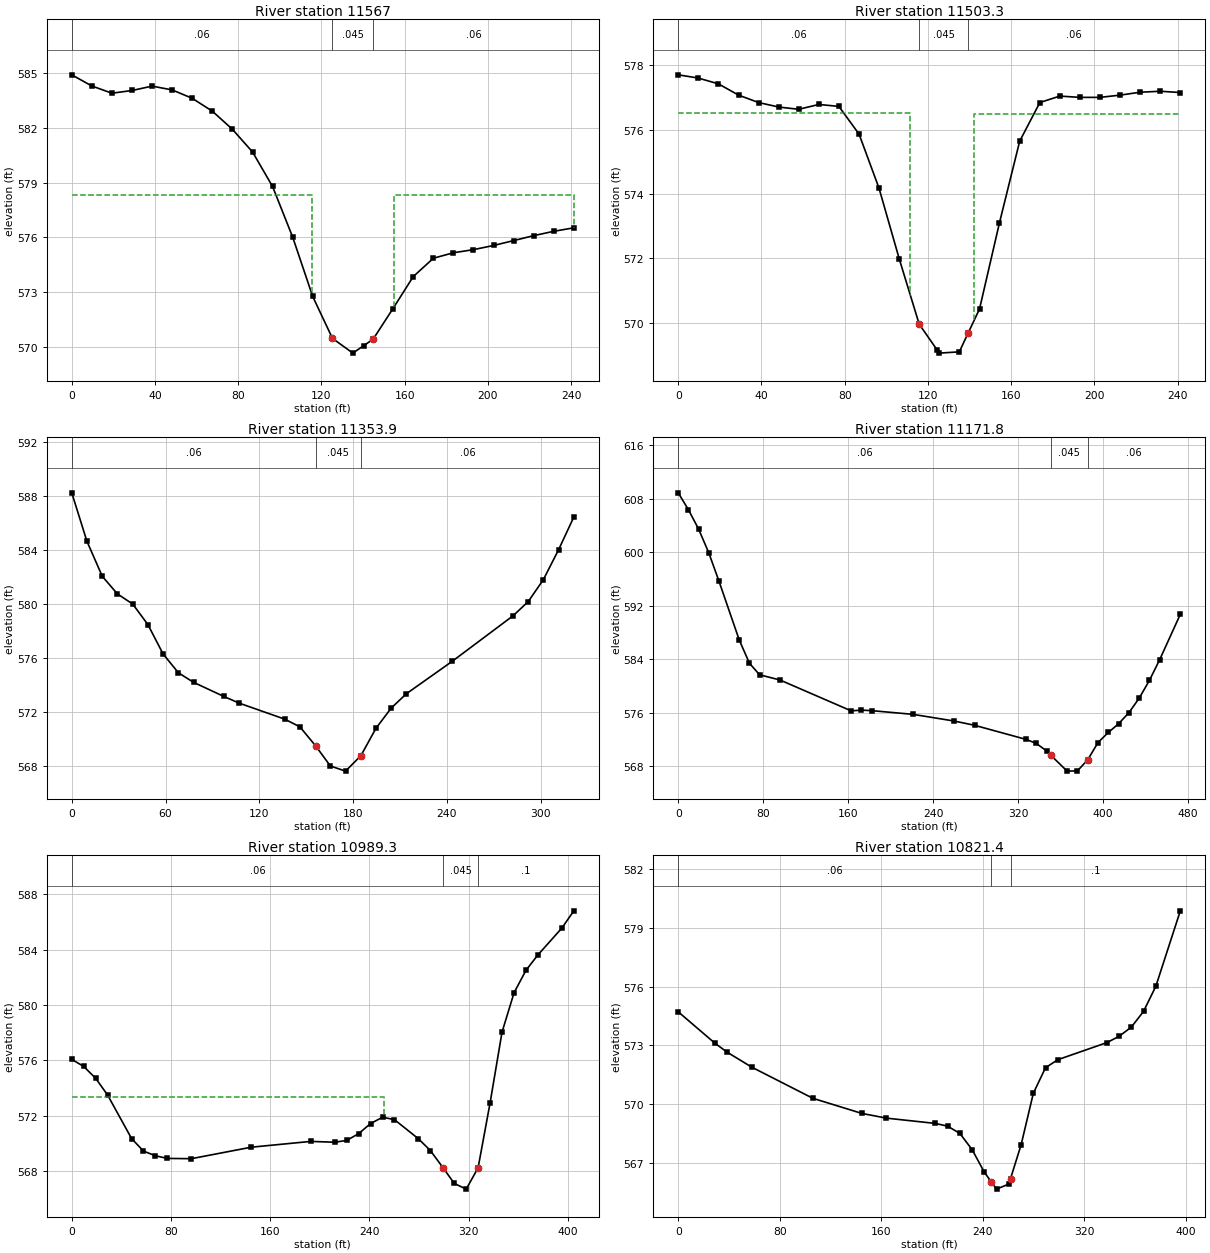
Type RM Length L Ch R = 1 ,11567   ,63.8,63.7,63.8
XS GIS Cut Line= 2
     1618620.663      570473.914     1618384.118      570521.657
#Sta/Elev= 27
       0  584.92     9.6  584.31    19.3  583.91      29  584.06    38.6   584.3
    48.3  584.09    57.9  583.63    67.6  582.92    77.2  581.93    86.9  580.68
    96.5  578.79   106.2     576   115.8  572.75   125.3  570.45   135.1  569.64
   140.3  570.05   144.8   570.4   154.4  572.09   164.1  573.84   173.8  574.85
   183.4  575.15     193  575.32   202.7  575.55   212.4  575.82     222  576.09
   231.7  576.33   241.3  576.52
#Mann= 3 , 0 , 0
       0     .06       0   125.3    .045       0   144.8     .06       0
#XS Ineff= 2 , 0
          115.49   578.3  154.93           578.3
Permanent Ineff=
       F       F
Bank Sta=125.3,144.8
XS Rating Curve= 0 ,0
Exp/Cntr=0.3,0.1

Type RM Length L Ch R = 1 ,11503.3 ,121.3,149.4,177.5
XS GIS Cut Line= 2
     1618648.875       570417.49      1618412.33      570465.233
#Sta/Elev= 28
       0   577.7     9.6   577.6    19.3  577.42      29  577.07    38.6  576.84
    48.3   576.7    57.9  576.63    67.6  576.78    77.2  576.72    86.9  575.86
    96.5  574.18   106.2  571.99   115.8  569.96   124.3  569.17   125.5  569.06
   135.1   569.1   139.3  569.68   144.8  570.43   154.4  573.11   164.1  575.64
   173.8  576.84   183.4  577.04     193     577   202.7     577   212.4  577.07
     222  577.16   231.7  577.19   241.3  577.15
#Mann= 3 , 0 , 0
       0     .06       0   115.8    .045       0   139.3     .06       0
#XS Ineff= 2 , 0
          111.62  576.52  142.25          576.48
Permanent Ineff=
       F       F
Bank Sta=115.8,139.3
XS Rating Curve= 0 ,0
Exp/Cntr=0.3,0.1

Type RM Length L Ch R = 1 ,11353.9 ,184.7,182.1,178.8
XS GIS Cut Line= 2
     1618705.299      570450.042     1618505.646      570198.306
#Sta/Elev= 26
       0  588.22     9.7  584.63    19.5  582.04    29.2  580.73      39  579.98
    48.7  578.46    58.4  576.29    68.2  574.89    77.9  574.18    97.4  573.13
   107.1  572.64   136.3  571.45     146  570.88     156  569.48   165.5  567.98
   175.2   567.6     185  568.74   194.7  570.78   204.5  572.28   214.2  573.34
   243.4  575.73   282.4  579.11   292.1  580.16   301.8  581.79   311.6  584.02
   321.3  586.43
#Mann= 3 , 0 , 0
       0     .06       0     156    .045       0     185     .06       0
Bank Sta=156,185
XS Rating Curve= 0 ,0
Exp/Cntr=0.3,0.1

Type RM Length L Ch R = 1 ,11171.8 ,174.5,182.5,190.2
XS GIS Cut Line= 3
     1618851.783      570474.275     1618845.273      570311.515
     1618626.089      570092.331
#Sta/Elev= 30
       0  608.89     9.6  606.36    19.2  603.46    28.8   599.9    38.3   595.7
    57.5  586.85    67.1  583.38    76.6  581.66    95.8  580.88   162.9  576.26
   172.6  576.37   182.3  576.29     221  575.74   259.8  574.74   279.1   574.1
   327.6  571.99   337.2  571.39   346.9  570.27   350.7  569.65   366.3  567.24
     376  567.28   385.7  568.94   395.4  571.52   405.1  573.03   414.7  574.32
   424.4  575.97   434.1  578.14   443.8  580.82   453.5  583.93   472.9  590.71
#Mann= 3 , 0 , 0
       0     .06       0   350.7    .045       0   385.7     .06       0
Bank Sta=350.7,385.7
XS Rating Curve= 0 ,0
Exp/Cntr=0.3,0.1

Type RM Length L Ch R = 1 ,10989.3 ,164.5,167.8,171.1
XS GIS Cut Line= 2
     1618971.141      570331.046     1618795.359      569966.463
#Sta/Elev= 30
       0  576.06     9.6  575.55    19.3  574.69    28.9  573.48    48.2  570.34
    57.8  569.43    67.5  569.09    77.1   568.9    96.4  568.88   144.6  569.71
   192.7  570.13     212  570.07   221.6   570.2   231.3  570.69   240.9  571.42
   250.6  571.88   260.2   571.7   279.5  570.32   289.1  569.47   299.4  568.22
   308.4  567.09     318  566.68   327.6  568.22   337.3  572.93   346.9  578.03
   356.6  580.88   366.2   582.5   375.8  583.61   395.1  585.55   404.8   586.8
#Mann= 3 , 0 , 0
       0     .06       0   299.4    .045       0   327.6      .1       0
#XS Ineff= 2 , 0
          251.41  573.31
Permanent Ineff=
       F       F
Bank Sta=299.4,327.6
XS Rating Curve= 0 ,0
Exp/Cntr=0.3,0.1

Type RM Length L Ch R = 1 ,10821.4 ,108,108.9,109.8
XS GIS Cut Line= 2
     1619062.287       570235.56     1618951.609      569855.786
#Sta/Elev= 26
       0  574.71    28.9  573.11    38.6  572.65    57.9  571.89   106.1   570.3
   144.7  569.53     164  569.29   202.6  569.02   212.3  568.88   221.9  568.51
   231.6  567.68   241.2  566.53   246.8  566.03   250.8  565.67   260.5  565.93
   261.8   566.2   270.2  567.94   279.8  570.56   289.4  571.86   299.1  572.27
   337.7  573.14   347.3  573.46     357  573.93   366.6  574.73   376.3  576.01
   395.6  579.86
#Mann= 3 , 0 , 0
       0     .06       0   246.8    .045       0   261.8      .1       0
Bank Sta=246.8,261.8
XS Rating Curve= 0 ,0
Exp/Cntr=0.3,0.1

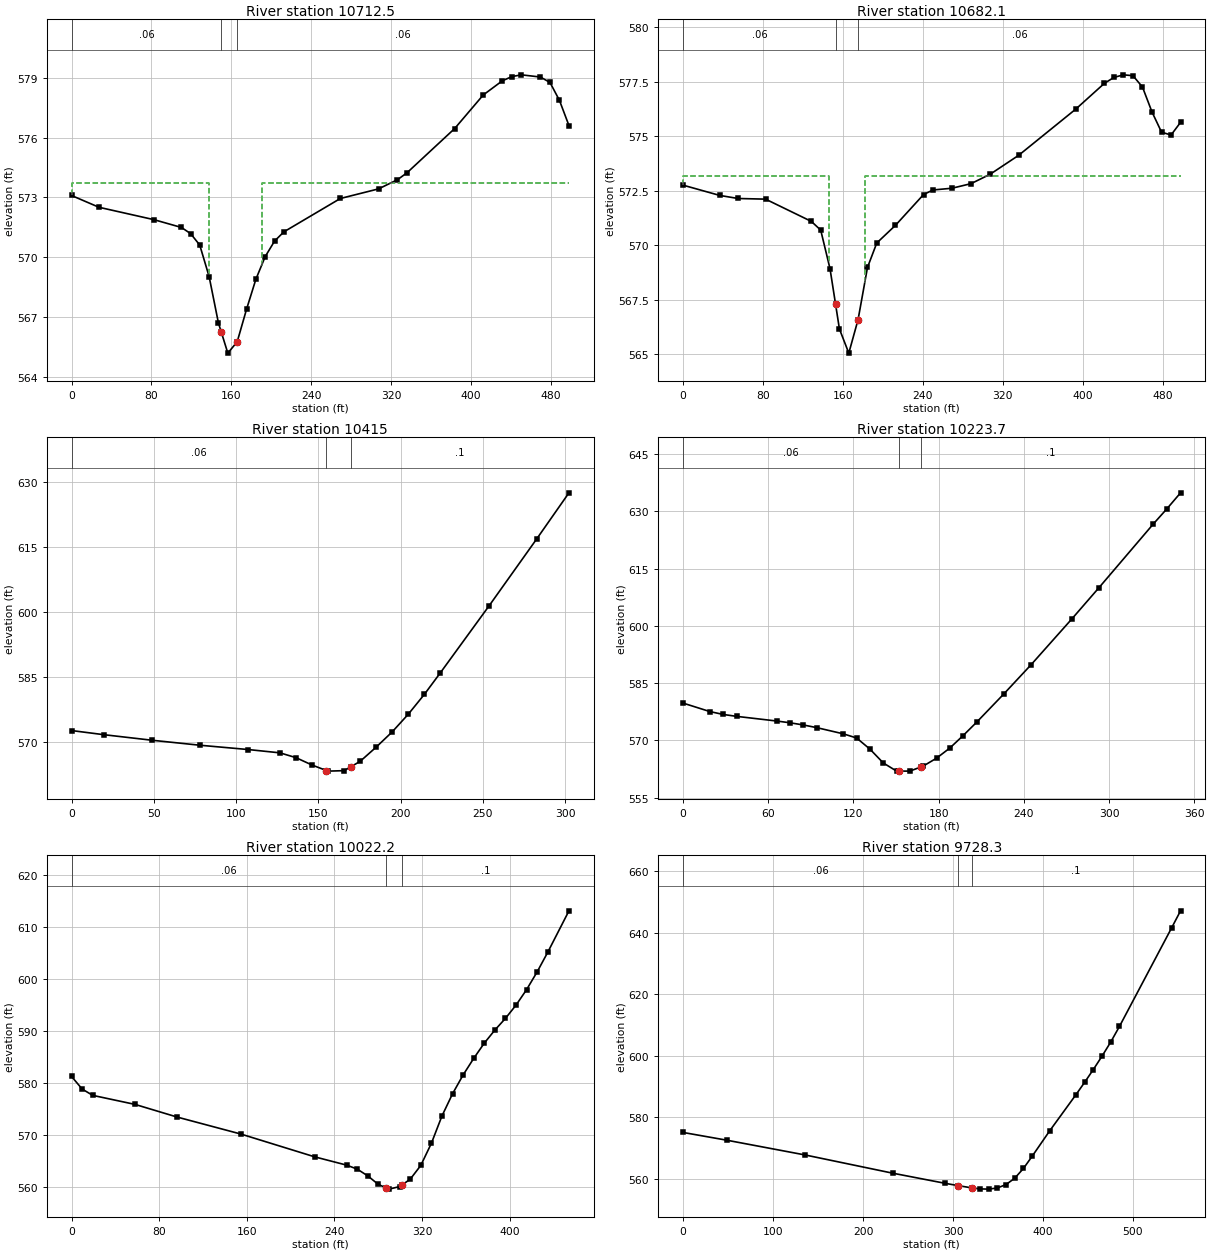
Type RM Length L Ch R = 1 ,10712.5 ,30.5,30.5,30.5
XS GIS Cut Line= 4
      1619114.37      570135.734     1619105.689      570007.696
     1619073.137      569890.508     1619057.946      569643.112
#Sta/Elev= 29
       0   573.1    27.5  572.51    82.5  571.89     110   571.5   119.2  571.19
   128.3  570.62   137.7  569.04     147  566.72   149.7  566.29   156.4  565.21
   165.8  565.78   175.1   567.4   184.5  568.91   193.8  570.04   203.2  570.82
   212.5  571.28     269  572.95   307.2  573.43   326.2  573.89   335.8  574.24
   383.4  576.45     412  578.13   431.1  578.84   440.6  579.05   450.2  579.14
   469.2  579.03   478.8  578.76   488.3  577.86   497.8   576.6
#Mann= 3 , 0 , 0
       0     .06       0   149.7    .045       0   165.8     .06       0
#XS Ineff= 2 , 0
          137.32  573.71  190.14          573.75
Permanent Ineff=
       F       F
Bank Sta=149.7,165.8
XS Rating Curve= 0 ,0
Exp/Cntr=0.3,0.1

Type RM Length L Ch R = 1 ,10682.1 ,236.9,267,296.6
XS GIS Cut Line= 4
     1619144.752      570131.393     1619136.071      570003.355
     1619103.519      569886.168     1619088.328      569638.772
#Sta/Elev= 30
       0  572.76    36.7  572.29      55  572.15    82.5  572.12   128.3   571.1
   137.7   570.7     147  568.93   152.5  567.32   156.4  566.17   165.8  565.06
   175.1   566.6   184.5  568.99   193.8  570.11   212.5  570.92   240.6  572.33
     250  572.54     269  572.62   288.1  572.83   307.2  573.26   335.8  574.13
     393  576.25   421.6  577.43   431.1   577.7   440.6  577.82   450.2  577.78
   459.7  577.26   469.2  576.12   478.8  575.19   488.3  575.06   497.8  575.64
#Mann= 3 , 0 , 0
       0     .06       0   152.5    .045       0   175.1     .06       0
#XS Ineff= 2 , 0
          145.77  573.17  181.69          573.17
Permanent Ineff=
       F       F
Bank Sta=152.5,175.1
XS Rating Curve= 0 ,0
Exp/Cntr=0.3,0.1

Type RM Length L Ch R = 1 ,10415   ,187.8,191.4,194.5
XS GIS Cut Line= 3
     1619181.644      570176.966     1619363.936      570064.119
     1619448.571      570040.248
#Sta/Elev= 21
       0  572.71    19.5  571.76    48.7  570.48      78  569.32   107.2  568.33
   126.7  567.56   136.4  566.45   146.2  564.74   154.9  563.48   155.9  563.34
   165.7  563.45   169.9  564.38   175.4   565.6   185.2   568.9   194.9  572.41
   204.6  576.46   214.4  581.05   224.2  586.07   253.5  601.37   282.8  617.01
   302.3   627.6
#Mann= 3 , 0 , 0
       0     .06       0   154.9    .045       0   169.9      .1       0
Bank Sta=154.9,169.9
XS Rating Curve= 0 ,0
Exp/Cntr=0.3,0.1

Type RM Length L Ch R = 1 ,10223.7 ,214.1,201.5,189
XS GIS Cut Line= 3
     1619207.252      570331.046     1619398.658      570252.921
     1619511.505      570163.946
#Sta/Elev= 28
       0  579.75    18.8  577.54    28.2  576.78    37.6  576.28    65.8  575.06
    75.2   574.6    84.6  574.03      94  573.33   112.8   571.7   122.2  570.61
   131.6  567.69     141  564.06   150.4  561.92   152.3  561.92   159.8  561.93
   167.3  562.99   169.2  563.26   178.5  565.31   187.9  567.98   197.3  571.26
   206.7  574.72   225.9  582.15   245.1  589.81   273.8  601.81     293  610.04
   331.3  626.75   340.9  630.74   350.4  634.88
#Mann= 3 , 0 , 0
       0     .06       0   152.3    .045       0   167.3      .1       0
Bank Sta=152.3,167.3
XS Rating Curve= 0 ,0
Exp/Cntr=0.3,0.1

Type RM Length L Ch R = 1 ,10022.2 ,307.1,293.9,280.6
XS GIS Cut Line= 2
     1619311.418      570653.963     1619582.252       570289.38
#Sta/Elev= 30
       0  581.25     9.7  578.83    19.3  577.62      58  575.88    96.6  573.44
   154.6  570.19   222.2   565.8   251.2  564.22   260.9  563.45   270.6  562.14
   280.2   560.5   286.9  559.89   289.9  559.61   299.6   560.1   301.9  560.44
   309.2   561.5   318.9  564.16   328.6  568.42   338.2  573.64   347.9  577.92
   357.5  581.52   367.2  584.71   376.9  587.65   386.5  590.15   396.2   592.4
   405.9  594.96   415.5  597.92   425.2  601.35   434.8  605.09   454.2  613.06
#Mann= 3 , 0 , 0
       0     .06       0   286.9    .045       0   301.9      .1       0
Bank Sta=286.9,301.9
XS Rating Curve= 0 ,0
Exp/Cntr=0.3,0.1

Type RM Length L Ch R = 1 ,9728.3  ,428.1,423.6,419.1
XS GIS Cut Line= 2
      1619703.78      570883.998     1619747.182      570332.782
#Sta/Elev= 23
       0  575.08    48.5  572.57   135.8  567.76   232.8  561.86     291  558.57
   305.6  557.81   320.6  557.09   329.8  556.75   339.5  556.67   349.2  557.04
   358.9  558.15   368.6  560.22   378.3   563.4     388  567.37   407.4  575.59
   436.5   587.3   446.2  591.34   455.9  595.51   465.6  599.87   475.3  604.47
     485  609.54   543.2  641.68   552.9   647.1
#Mann= 3 , 0 , 0
       0     .06       0   305.6    .045       0   320.6      .1       0
Bank Sta=305.6,320.6
XS Rating Curve= 0 ,0
Exp/Cntr=0.3,0.1

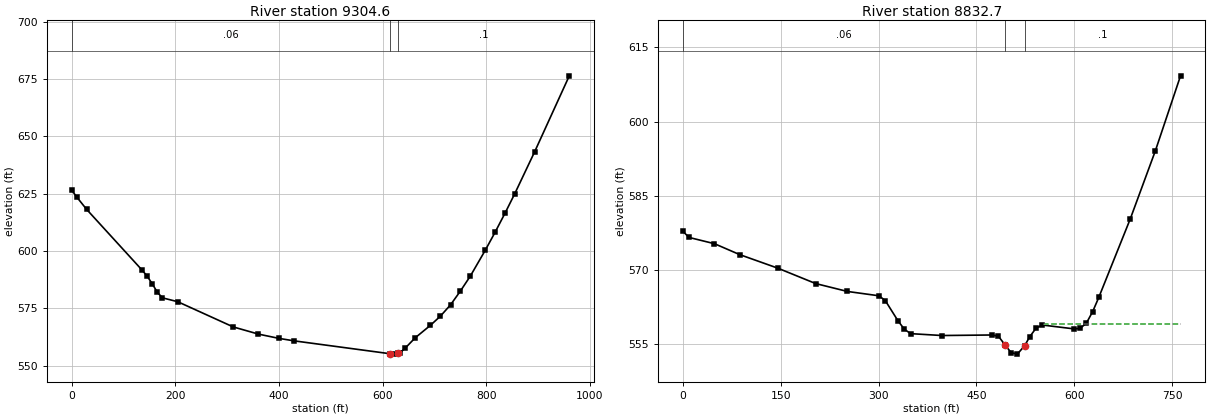
Type RM Length L Ch R = 1 ,9304.6  ,474.5,471.9,469.3
XS GIS Cut Line= 3
      1620183.38      571103.182     1620107.425      570376.185
     1620011.939      570167.852
#Sta/Elev= 30
       0  626.67     9.8  623.61    29.2  618.14   136.4  591.63   146.2  588.96
   155.9  585.65   165.7  581.99   175.4  579.62   204.7  577.95   311.9  566.95
   360.6  563.82   399.6  561.98   428.8   560.9   614.1  555.28   623.8   555.1
   629.1  555.45   633.5  555.74   643.2  557.62   662.7  562.18     692  567.61
   711.5  571.65     731  576.57     750  582.56   769.2   589.1   797.8  600.27
   816.9  608.18     836  616.46   855.1  625.09   893.3  643.29   960.1  676.37
#Mann= 3 , 0 , 0
       0     .06       0   614.1    .045       0   629.1      .1       0
Bank Sta=614.1,629.1
XS Rating Curve= 0 ,0
Exp/Cntr=0.3,0.1

Type RM Length L Ch R = 1 ,8832.7  ,8790,8832.7,8869.8
XS GIS Cut Line= 3
     1620567.495      570940.421     1620593.537       570601.88
      1620498.05      570189.553
#Sta/Elev= 30
       0  577.82     9.7  576.57    48.5  575.31    87.3   573.1   145.5  570.37
   203.7  567.25   252.2  565.66   300.7  564.78   310.4   563.8   329.8  559.72
   339.5  558.03   349.2  557.13   397.3  556.75   474.2  556.86   483.8  556.59
   493.4  554.93   503.1   553.3   512.7  552.99     524  554.71   531.9  556.55
   541.5  558.26   551.2  558.87   599.3   558.1   608.9  558.19   618.5  559.25
   628.1  561.57   637.7  564.51   685.8  580.33   724.3  594.11   762.8  609.24
#Mann= 3 , 0 , 0
       0     .06       0   493.4    .045       0     524      .1       0
#XS Ineff= 2 , 0
                          553.24           559.1
Permanent Ineff=
       F       F
Bank Sta=493.4,524
XS Rating Curve= 0 ,0
Exp/Cntr=0.3,0.1

Chan Stop Cuts=-1
Use User Specified Reach Order=0
Composite Channel Slope=5